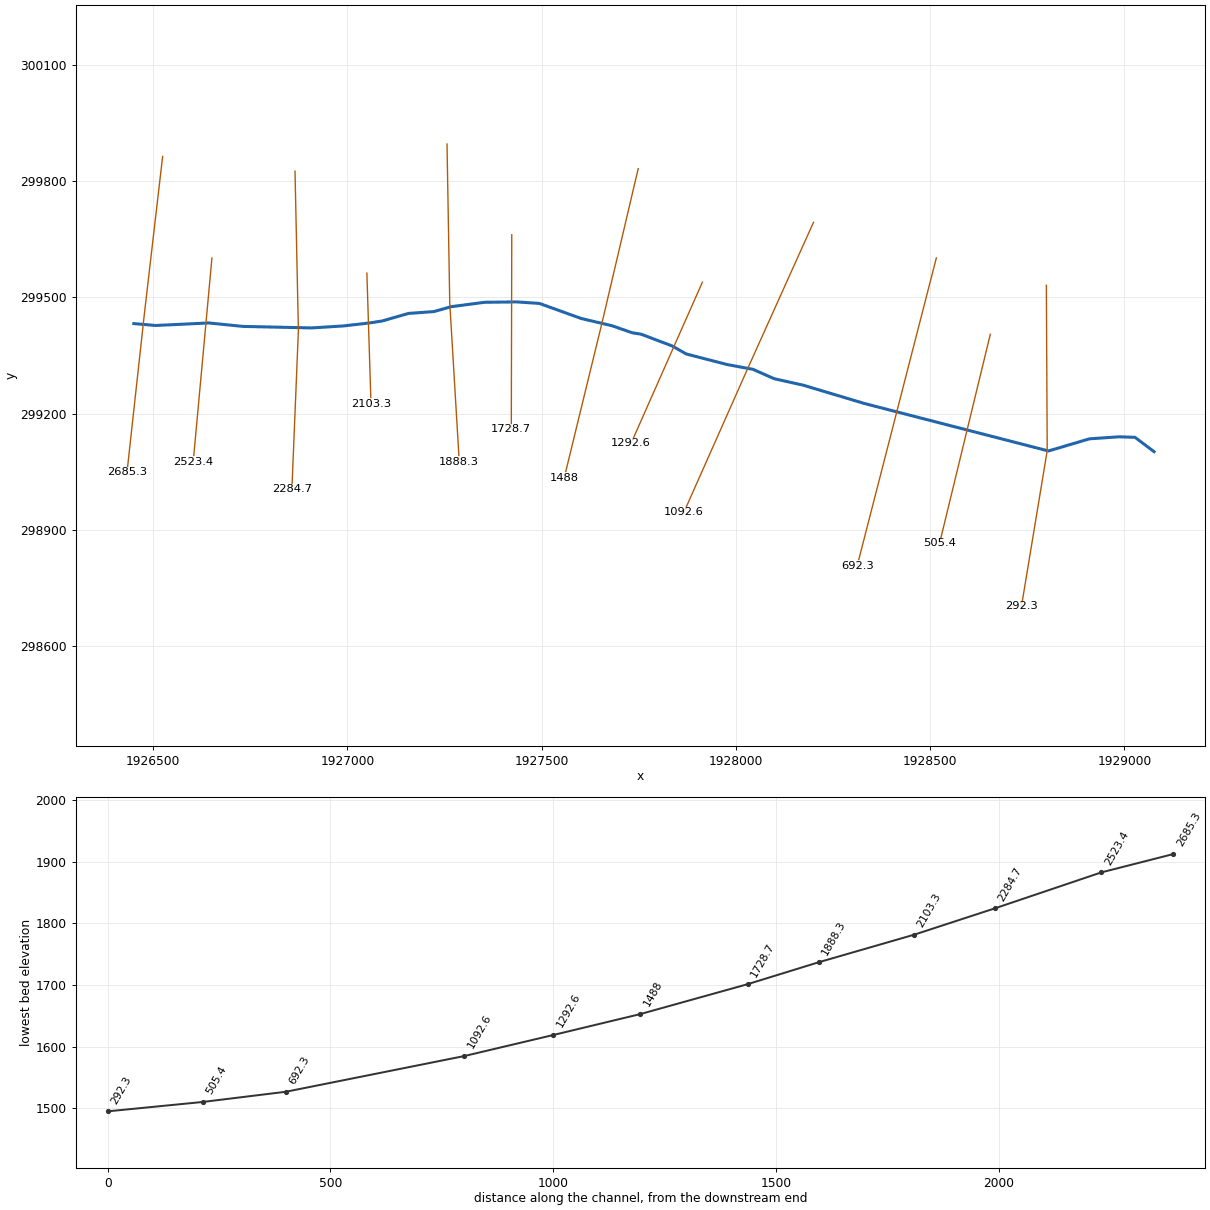
--- StnfrdBrnc.prj (project) ---

Proj Title=StnfrdBrnc
Current Plan=p01
Geom File=g01
Flow File=f01
Plan File=p01
DSS Export Rating Curves=0
DSS Export Rating Curve Sorted=0
DSS Export Volume Flow Curves=0
DXF OffsetX=0
DXF OffsetY=0
DXF ScaleX=0
DXF ScaleY=0

--- StnfrdBrnc.p01 (plan) ---

Plan Title=Floodplain
Program Version=4.00
Geom File=g01
Flow File=f01
K Sum by GR=0
Std Step Tol=0.01
Critical Tol=0.01
Num of Std Step Trials=20
Max Error Tol=0.3
Flow Tol Ratio=0.001
Split Flow NTrial=30
Split Flow Tol=0.02
Split Flow Ratio=0.02
Log Output Level=0
Friction Slope Method=1
Unsteady Friction Slope Method=2
Unsteady Bridges Friction Slope Method=1
Global Log Level=0
CheckData=False
Run HTab=0
Run UNet=0
Run PostProcess=0
UNET Theta=0
UNET Theta Warmup=0
UNET ZTol=0
UNET ZSATol=0
UNET MxIter=0
UNET MaxInSteps=0
UNET DtIC=0
UNET DtMin=0
UNET MaxCRTS=0
UNET WFStab=0
UNET SFStab=0
UNET WFX=0
UNET SFX=0
UNET DSS MLevel=0
UNET DZMax Abort=0
UNET Convert EG Bridges=0
UNET Use Existing IB Tables=0
UNET Froude Limit=0
UNET Froude Power=0
Write IC File=0
Echo Input=False
Echo Output=False
Write Detailed=0

--- StnfrdBrnc.f01 (steady flow) ---

Flow Title=NFF Regression Equation
Program Version=4.00
Number of Profiles=1
Profile Names=P100yr
River Rch & RM=StnfrdBrnc,Main      ,2685.3
527.4236
River Rch & RM=StnfrdBrnc,Main      ,2284.7
533.5893
River Rch & RM=StnfrdBrnc,Main      ,292.3
592.3183
Boundary for River Rch & Prof#=StnfrdBrnc,Main      ,1
Up Type=0
Dn Type=3
Dn Slope=0.100639

--- StnfrdBrnc.g01 (geometry) ---

Geom Title=USGS 3m DEM
Program Version=4.00

River Reach=StnfrdBrnc     ,Main
Reach XY= 30
     1926450.354      299432.143     1926506.497      299427.303
     1926643.460      299433.813     1926731.229      299424.883
     1926908.047      299421.011     1926990.648      299426.174
     1927059.215      299434.129     1927090.191      299438.969
     1927156.981      299458.329     1927222.804      299463.169
     1927267.331      299475.752     1927353.392      299487.104
     1927435.774      299488.061     1927494.388      299484.152
     1927601.896      299445.294     1927680.649      299426.839
     1927732.750      299408.603     1927756.085      299404.839
     1927836.017      299374.548     1927872.155      299353.898
     1927976.697      299326.794     1928044.285      299314.203
     1928098.760      299290.068     1928174.307      299273.134
     1928330.610      299226.241     1928804.730      299103.797
     1928910.235      299135.057     1928985.782      299140.266
     1929027.463      299138.963     1929076.508      299101.964

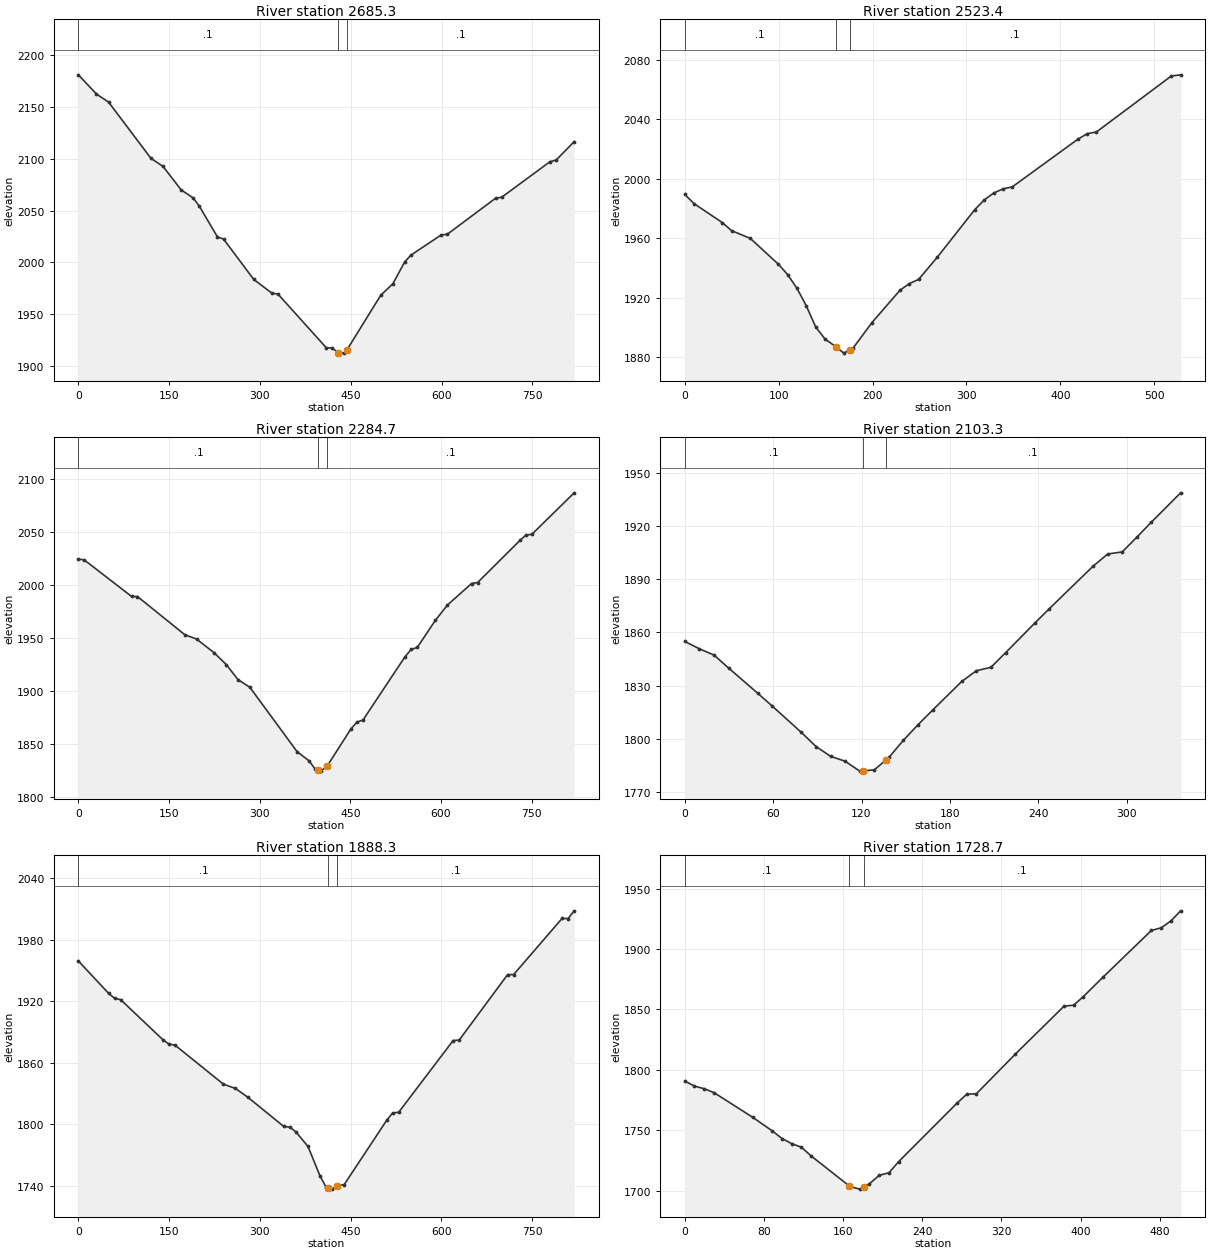
Type RM Length L Ch R = 1 ,2685.3,161.4,161.8,162.1
XS GIS Cut Line= 3
     1926524.496      299863.153     1926477.365      299456.254
     1926432.797      299049.276
#Sta/Elev= 30
       0 2180.79    30.0 2162.26    50.0 2154.50   119.9 2100.34   139.9 2092.54
   169.8 2069.98   189.8 2062.12   199.8 2054.28   229.8 2024.63   239.8 2022.58
   289.7 1983.68   319.7 1970.42   329.7 1969.56   409.6 1917.80   419.6 1917.64
     429 1912.93   429.6 1912.63   439.6 1912.72     444 1916.06   499.5 1968.37
   519.5 1979.44   539.4 2000.78   549.4 2007.06   599.4 2026.53   609.3 2027.10
   689.2 2061.87   699.2 2062.79   779.1 2097.10   789.1 2098.57   819.0 2116.38
#Mann= 3 , 0 , 0
       0     0.1       0     429   0.045       0     444     0.1       0
Bank Sta=     429,     444
Exp/Cntr=0.3,0.1

Type RM Length L Ch R = 1 ,2523.4,236,238.5,240.1
XS GIS Cut Line= 2
     1926651.361      299601.105     1926603.123      299075.195
#Sta/Elev= 30
       0 1989.44    10.0 1983.22    39.9 1970.57    49.8 1965.14    69.8 1959.90
    99.6 1942.60   109.6 1935.52   119.6 1926.25   129.5 1914.43   139.5 1900.30
   149.5 1892.18   160.6 1887.25   169.4 1882.80   175.6 1884.98   179.4 1886.32
   199.3 1903.30   229.2 1925.08   239.2 1929.52   249.1 1932.39   269.0 1947.33
   308.9 1979.29   318.9 1985.72   328.8 1990.34   338.8 1993.20   348.8 1994.55
   418.5 2026.52   428.5 2030.29   438.4 2031.44   518.2 2069.09   528.1 2069.86
#Mann= 3 , 0 , 0
       0     0.1       0   160.6   0.045       0   175.6     0.1       0
Bank Sta=   160.6,   175.6
Exp/Cntr=0.3,0.1

Type RM Length L Ch R = 1 ,2284.7,181.1,181.3,182.5
XS GIS Cut Line= 3
     1926865.235      299825.276     1926873.912      299414.401
     1926857.217      299005.500
#Sta/Elev= 30
       0 2024.34     9.8 2023.48    88.1 1989.08    97.8 1989.00   176.1 1953.06
   195.7 1948.89   225.0 1935.89   244.6 1924.96   264.2 1910.72   283.8 1903.48
   362.0 1842.78   381.6 1834.29   391.4 1826.74   396.9 1825.50   401.2 1824.53
   411.9 1829.54   450.9 1864.30   460.9 1870.70   470.9 1872.69   540.7 1932.51
   550.7 1939.25   560.7 1941.00   590.6 1966.57   610.6 1981.00   650.5 2001.28
   660.5 2002.20   730.4 2041.80   740.4 2046.91   750.3 2047.65   820.2 2086.70
#Mann= 3 , 0 , 0
       0     0.1       0   396.9   0.045       0   411.9     0.1       0
Bank Sta=   396.9,   411.9
Exp/Cntr=0.3,0.1

Type RM Length L Ch R = 1 ,2103.3,214.7,214.7,215.3
XS GIS Cut Line= 2
     1927050.205      299562.280     1927060.794      299225.791
#Sta/Elev= 30
       0 1854.93     9.9 1850.75    19.8 1847.25    29.7 1839.94    49.5 1825.68
    59.4 1818.42    79.2 1803.53    89.1 1795.60    99.0 1790.06   108.9 1787.29
   118.8 1781.70   121.3 1781.88   128.7 1782.42   136.3 1787.79   138.6 1789.42
   148.5 1799.20   158.4 1807.90   168.3 1816.16   188.1 1832.36   198.0 1838.38
   207.9 1840.33   217.8 1848.52   237.6 1865.22   247.5 1873.38   277.2 1897.36
   287.2 1904.30   297.0 1905.44   307.0 1913.80   316.8 1922.24   336.7 1938.82
#Mann= 3 , 0 , 0
       0     0.1       0   121.3   0.045       0   136.3     0.1       0
Bank Sta=   121.3,   136.3
Exp/Cntr=0.3,0.1

Type RM Length L Ch R = 1 ,1888.3,160.2,159.4,158.1
XS GIS Cut Line= 3
     1927256.500      299895.083     1927263.552      299485.722
     1927287.978      299076.504
#Sta/Elev= 30
       0 1959.36    49.9 1927.80    59.9 1922.89    69.9 1921.57   139.8 1882.49
   149.8 1878.23   159.8 1877.22   239.7 1839.20   259.6 1835.00   279.6 1826.66
   339.5 1797.94   349.5 1797.30   359.5 1792.71   379.5 1778.44   399.4 1749.73
   409.4 1738.75   412.9 1738.08   419.4 1736.83   427.9 1739.80   439.4 1741.32
   509.4 1803.76   519.4 1811.11   529.4 1811.75   619.4 1881.73   629.4 1882.16
   709.4 1945.96   719.4 1946.04   799.4 2000.76   809.4 2000.68   819.4 2008.19
#Mann= 3 , 0 , 0
       0     0.1       0   412.9   0.045       0   427.9     0.1       0
Bank Sta=   412.9,   427.9
Exp/Cntr=0.3,0.1

Type RM Length L Ch R = 1 ,1728.7,245.9,240.8,235.4
XS GIS Cut Line= 2
     1927423.166      299661.109     1927421.990      299159.905
#Sta/Elev= 30
       0 1790.72     9.8 1786.50    19.7 1784.32    29.5 1781.13    68.8 1760.62
    88.4 1749.44    98.3 1743.11   108.1 1738.88   117.9 1735.92   127.8 1728.66
   165.7 1704.24   167.1 1703.35   176.9 1701.25   180.7 1702.99   186.7 1705.74
   196.6 1712.68   206.4 1714.81   216.2 1724.03   275.2 1772.46   285.0 1779.77
   294.8 1780.23   334.1 1812.98   383.3 1852.63   393.1 1853.50   402.9 1860.61
   422.6 1876.55   471.7 1915.35   481.6 1917.51   491.4 1923.22   501.2 1931.56
#Mann= 3 , 0 , 0
       0     0.1       0   165.7   0.045       0   180.7     0.1       0
Bank Sta=   165.7,   180.7
Exp/Cntr=0.3,0.1

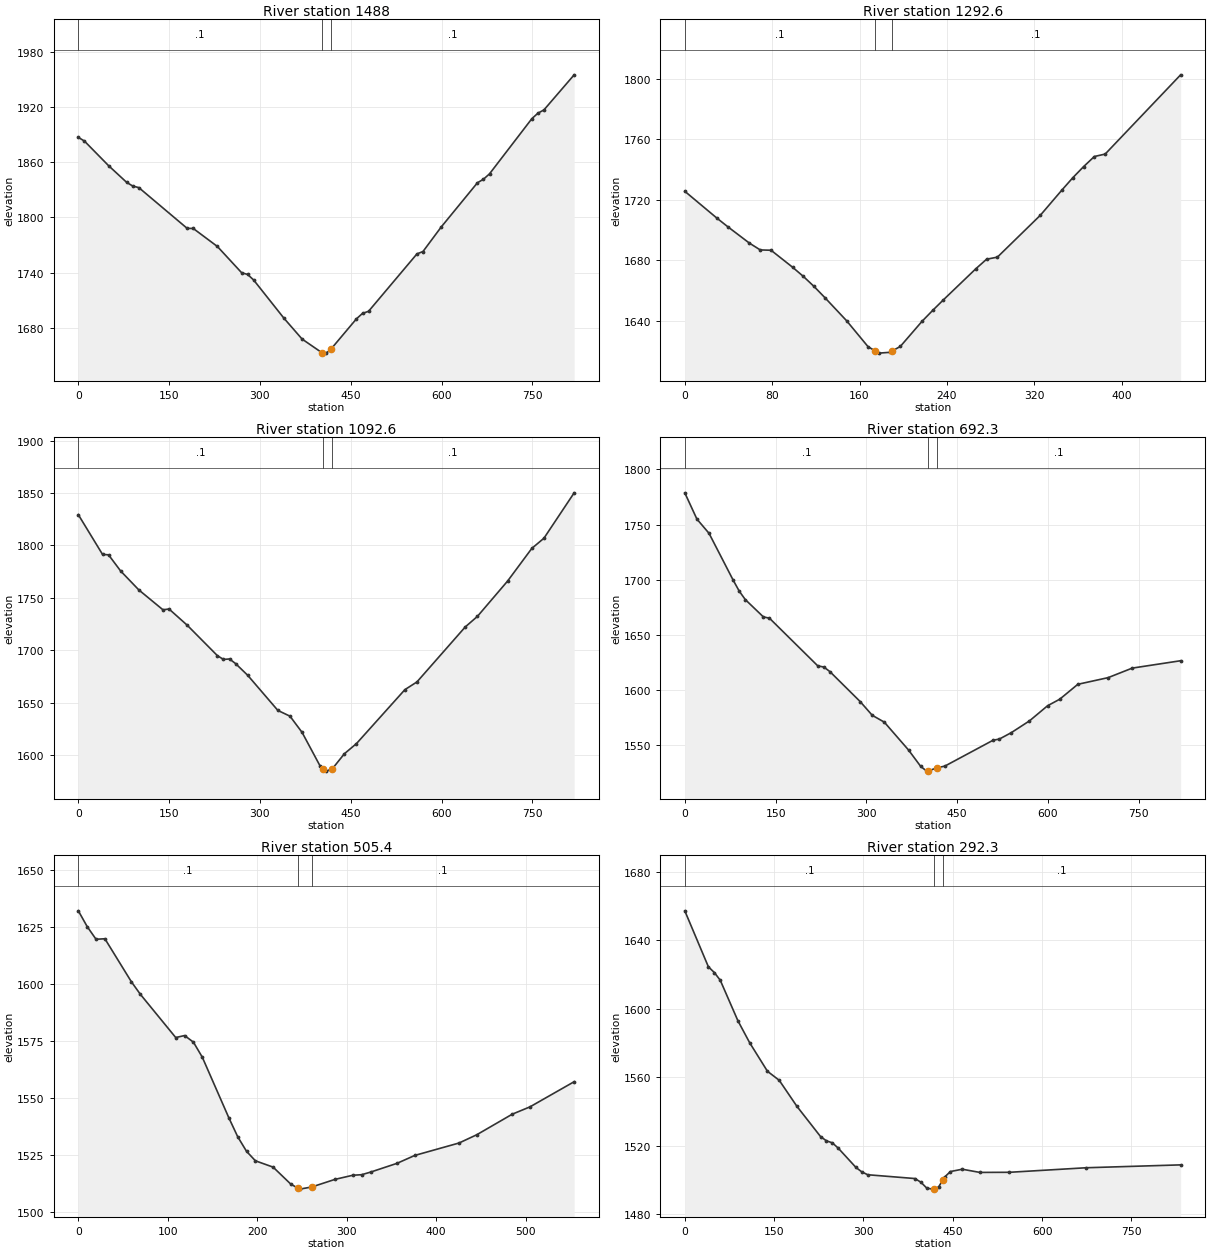
Type RM Length L Ch R = 1 ,1488,199.5,195.3,191.3
XS GIS Cut Line= 3
     1927748.577      299831.511     1927655.145      299432.816
     1927558.314      299034.910
#Sta/Elev= 30
       0 1886.95    10.0 1882.96    49.9 1856.26    79.9 1838.05    89.9 1834.10
    99.9 1832.40   179.8 1788.14   189.8 1788.05   229.7 1768.48   269.7 1740.01
   279.7 1738.09   289.6 1732.09   339.6 1690.62   369.6 1667.97     402 1653.33
   409.5 1652.70     417 1656.83   459.4 1689.95   469.4 1695.83   479.4 1698.11
   559.3 1760.41   569.3 1763.02   599.3 1789.55   659.2 1837.63   669.2 1841.52
   679.2 1847.34   749.1 1907.21   759.1 1913.18   769.1 1916.76   819.0 1954.84
#Mann= 3 , 0 , 0
       0     0.1       0     402   0.045       0     417     0.1       0
Bank Sta=     402,     417
Exp/Cntr=0.3,0.1

Type RM Length L Ch R = 1 ,1292.6,199.9,199.7,199.7
XS GIS Cut Line= 2
     1927913.781      299538.749     1927730.242      299123.433
#Sta/Elev= 30
       0 1725.56    29.6 1707.72    39.5 1702.08    59.2 1691.32    69.1 1686.84
    79.0 1686.63    98.7 1675.43   108.6 1669.34   118.4 1662.70   128.3 1655.34
   148.1 1640.16   167.8 1622.99   174.6 1620.05   177.7 1618.71   187.6 1619.23
   189.6 1620.03   197.4 1623.13   217.2 1639.65   227.0 1646.90   236.9 1653.93
   266.5 1674.38   276.4 1680.71   286.3 1682.08   325.7 1709.79   345.5 1726.47
   355.4 1734.54   365.2 1741.81   375.1 1748.52   385.0 1750.12   454.1 1802.44
#Mann= 3 , 0 , 0
       0     0.1       0   174.6   0.045       0   189.6     0.1       0
Bank Sta=   174.6,   189.6
Exp/Cntr=0.3,0.1

Type RM Length L Ch R = 1 ,1092.6,396.4,400.4,404.2
XS GIS Cut Line= 3
     1928199.848      299693.174     1928031.968      299319.660
     1927866.091      298945.262
#Sta/Elev= 30
       0 1829.29    40.0 1791.37    49.9 1791.00    69.9 1775.56    99.9 1757.52
   139.8 1738.51   149.8 1739.30   179.8 1723.84   229.7 1694.76   239.7 1691.17
   249.7 1691.60   259.7 1687.21   279.7 1676.05   329.6 1642.47   349.6 1636.99
   369.6 1621.50   399.5 1589.26   404.4 1586.95   409.5 1584.54   419.4 1586.67
   439.5 1601.15   459.4 1610.81   539.4 1662.31   559.3 1669.66   639.2 1722.20
   659.2 1732.23   709.1 1765.99   749.1 1797.16   769.1 1806.85   819.0 1850.17
#Mann= 3 , 0 , 0
       0     0.1       0   404.4   0.045       0   419.4     0.1       0
Bank Sta=   404.4,   419.4
Exp/Cntr=0.3,0.1

Type RM Length L Ch R = 1 ,692.3,186.6,186.9,187.2
XS GIS Cut Line= 3
     1928516.075      299601.403     1928414.232      299204.769
     1928312.388      298808.136
#Sta/Elev= 30
       0 1778.83    20.0 1755.03    40.0 1742.15    79.9 1699.66    89.9 1689.74
    99.9 1682.08   129.8 1666.35   139.8 1665.21   219.7 1621.94   229.7 1620.92
   239.7 1616.76   289.6 1589.65   309.6 1577.18   329.6 1570.93   369.6 1545.67
   389.5 1530.96   399.5 1526.55     402 1526.78     417 1529.59   429.5 1531.09
   509.4 1554.61   519.4 1555.57   539.3 1561.42   569.3 1572.09   599.3 1585.84
   619.2 1591.70   649.2 1605.26   699.2 1611.29   739.1 1619.94   819.0 1626.62
#Mann= 3 , 0 , 0
       0     0.1       0     402   0.045       0     417     0.1       0
Bank Sta=     402,     417
Exp/Cntr=0.3,0.1

Type RM Length L Ch R = 1 ,505.4,207.4,213,214.7
XS GIS Cut Line= 2
     1928654.997      299404.624     1928524.402      298865.772
#Sta/Elev= 30
       0 1631.91     9.9 1625.00    19.8 1619.45    29.7 1619.67    59.4 1600.77
    69.3 1595.36   108.9 1576.38   118.8 1577.26   128.7 1574.36   138.6 1567.78
   168.3 1541.21   178.2 1532.92   188.1 1526.51   198.0 1522.37   217.8 1519.60
   237.6 1512.14   245.8 1510.33   247.5 1509.96   260.8 1510.88   287.1 1514.25
   306.9 1516.04   316.8 1516.28   326.7 1517.41   356.4 1521.27   376.2 1524.73
   425.7 1530.17   445.5 1533.79   485.2 1542.80   505.0 1546.01   554.4 1557.03
#Mann= 3 , 0 , 0
       0     0.1       0   245.8   0.045       0   260.8     0.1       0
Bank Sta=   245.8,   260.8
Exp/Cntr=0.3,0.1

Type RM Length L Ch R = 1 ,292.3,307.2,292.3,281.2
XS GIS Cut Line= 3
     1928799.275      299530.821     1928801.451      299104.593
     1928735.235      298703.527
#Sta/Elev= 30
       0 1657.11    39.6 1624.47    49.6 1621.10    59.5 1616.65    89.2 1592.97
   109.0 1580.12   138.8 1563.51   158.6 1558.24   188.3 1543.05   228.0 1525.41
   237.9 1522.92   247.8 1521.76   257.7 1518.65   287.5 1507.38   297.4 1504.77
   307.3 1503.14   386.6 1500.92   396.5 1498.78   406.4 1495.34   416.3 1494.75
   418.7 1495.05   426.2 1495.97   433.7 1500.30   436.2 1501.74   446.1 1505.01
   465.9 1506.36   495.6 1504.50   545.2 1504.57   674.1 1507.22   832.7 1508.90
#Mann= 3 , 0 , 0
       0     0.1       0   418.7   0.045       0   433.7     0.1       0
Bank Sta=   418.7,   433.7
Exp/Cntr=0.3,0.1